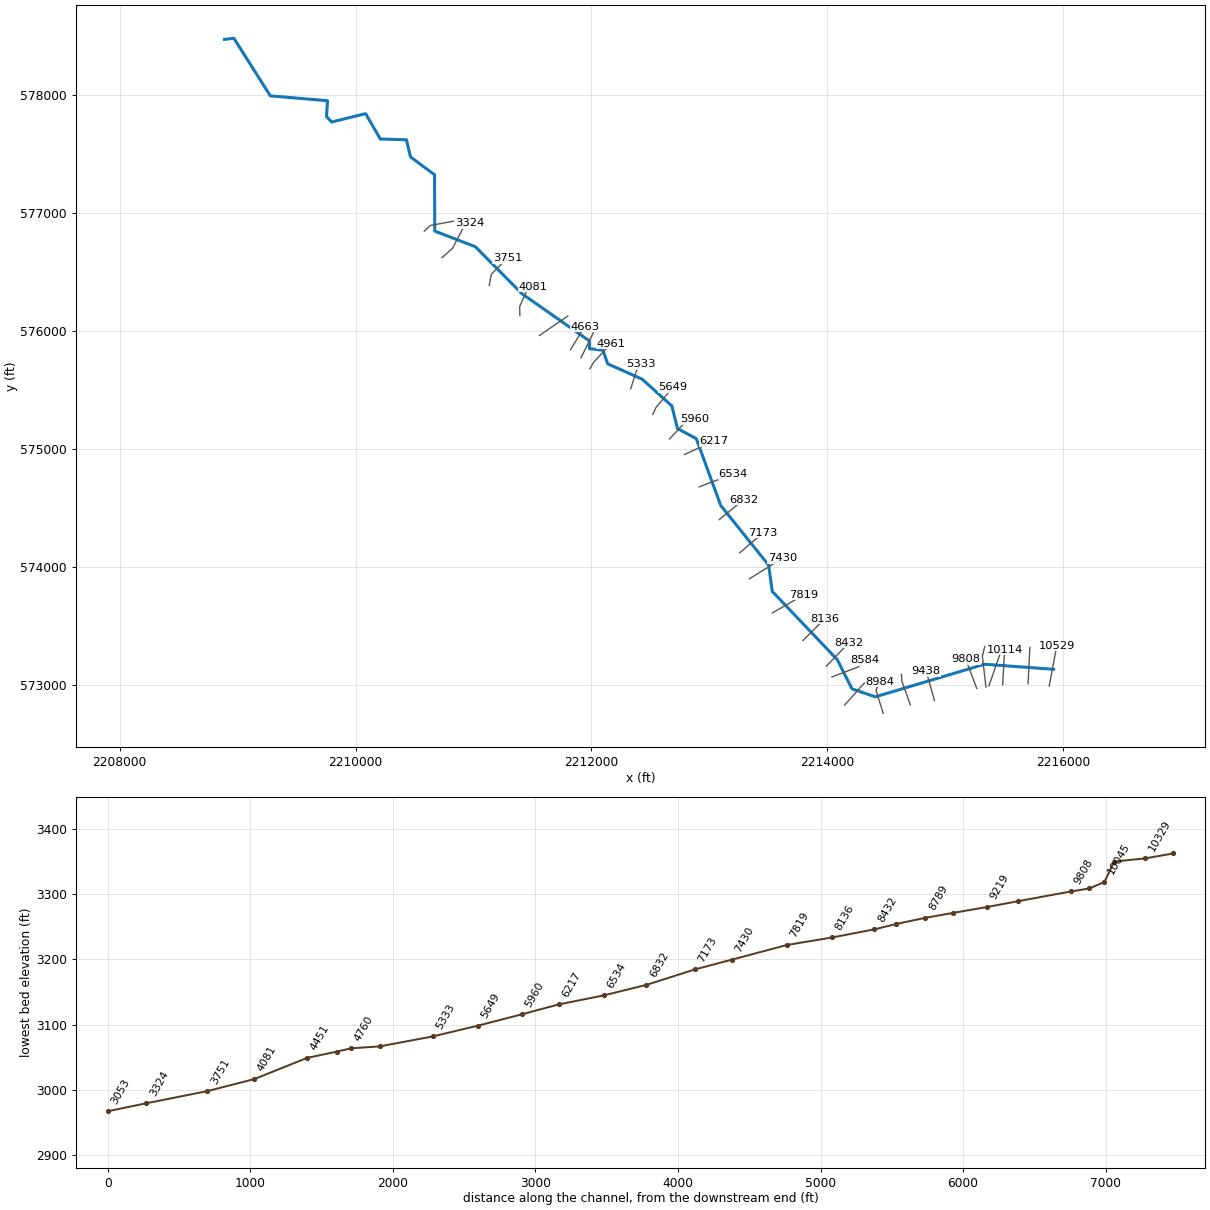
--- HEWETTFK.prj (project) ---

Proj Title=HEWETTFK
Current Plan=p01
Default Exp/Contr=0,0
English Units
Geom File=g01
Flow File=f01
Plan File=p01
BEGIN DESCRIPTION:
----------MODEL BY WOOD PLC 2022----------
AFH study
Randolph County, WV
HEC-RAS Version: RAS 6.2
Vertical Datum: NAVD88
Projection: NAD 1983 StatePlane West Virginia S FIPS 4702 (US Feet)
Terrain: 1-meter LIDAR (FEMA Region III 3DEP collected 2016-2018)
Land Use: 2019 NLCD
Hydrologic Method:
WV SIR2010-5033 regression equations
Additional Model Notes:
None
END DESCRIPTION:
DSS Export Rating Curves= 0
DSS Export Rating Curve Sorted= 0
DSS Export Volume Flow Curves= 0
DXF OffsetX= 0
DXF OffsetY= 0
DXF ScaleX= 0
DXF ScaleY= 0

--- HEWETTFK.p01 (plan) ---

Plan Title=Floodplain
Program Version=6.20
Short Identifier=Floodplain
Geom File=g01
Flow File=f01
Subcritical Flow
K Sum by GR= 0
Std Step Tol= 0.01
Critical Tol= 0.01
Num of Std Step Trials= 20
Max Error Tol= 0.3
Flow Tol Ratio= 0.001
Split Flow NTrial= 30
Split Flow Tol= 0.02
Split Flow Ratio= 0.02
Log Output Level= 0
Friction Slope Method= 1
Unsteady Friction Slope Method= 2
Unsteady Bridges Friction Slope Method= 1
Parabolic Critical Depth
Global Vel Dist= 0 , 0 , 0
Global Log Level= 0
CheckData=True
Encroach Param=-1 ,0,0, 0
Mapping Interval=1HOUR
Computation Time Step Use Courant=        0
Computation Time Step Use Time Series=    0
Computation Time Step Count To Double=0
Computation Time Step Max Doubling=0
Computation Time Step Max Halving=0
Computation Time Step Residence Courant=0
Run HTab= 0
Run UNet= 0
Run Sediment= 0
Run PostProcess= 0
Run WQNet= 0
Run RASMapper=-1
UNET Theta= 0
UNET Theta Warmup= 0
UNET ZTol= 0
UNET ZSATol= 0
UNET MxIter= 0
UNET Max Iter WO Improvement= 0
UNET MaxInSteps= 0
UNET DtIC= 0
UNET DtMin= 0
UNET MaxCRTS= 0
UNET WFStab= 0
UNET SFStab= 0
UNET WFX= 1
UNET SFX= 1
UNET Gravity=32.174
UNET 1D Methodology=Finite Difference
UNET DSS MLevel= 1
UNET Pardiso=0
UNET DZMax Abort= 0
UNET Use Existing IB Tables= 0
UNET Froude Reduction=False
UNET Froude Limit= 0
UNET Froude Power= 0
UNET D1 Cores= 0
UNET WindReference=Eulerian
UNET WindDragFormulation=Hsu (1988)
UNET D2 Coriolis=0
UNET D2 Cores= 0
UNET D2 Theta= 1
UNET D2 Theta Warmup= 1
UNET D2 Z Tol= 0.01
UNET D2 Volume Tol= 0.01
UNET D2 Max Iterations= 20
UNET D2 Equation= 0
UNET D2 RampUpFraction=0.1
UNET D2 TimeSlices= 1
UNET D2 Turbulence Formulation=Non-Conservative (original)
UNET D2 Eddy Viscosity=0.3
UNET D2 Transverse Eddy Viscosity=0.1
UNET D2 Smagorinsky Mixing=0
UNET D2 BCVolumeCheck=0
UNET D2 Cores=0
UNET D2 SolverType=PARDISO (Direct)
UNET D2 Minimum Iterations= 2147483647
UNET D2 Maximum Iterations= 2147483647
UNET D2 Restart Number= 10
UNET D2 Relaxation Coeff=1.3
UNET D2 SOR Precondition Iterations= 10
UNET D2 ILUT Maximum Fill= 8
UNET D2 ILUT Tolerance=1E-08
UNET D1D2 MaxIter= 0
UNET D1D2 ZTol=0.01
UNET D1D2 QTol=0.1
UNET D1D2 MinQTol=1
Write IC File= 0
Write IC File at Fixed DateTime=0
Write IC File at Sim End=0
Echo Input=False
Echo Parameters=False
Echo Output=False
Write Detailed= 0
HDF Write Warmup=0
HDF Write Time Slices=0
HDF Flush=0
HDF Compression= 1
HDF Chunk Size= 1
HDF Spatial Parts= 1
HDF Use Max Rows=0
HDF Fixed Rows= 1
Calibration Method= 0
Calibration Iterations= 20
Calibration Max Change=0.05
Calibration Tolerance=0.2
Calibration Maximum=1.5
Calibration Minimum=0.5
Calibration Optimization Method= 1
WQ AD Non Conservative
WQ ULTIMATE=-1
WQ Max Comp Step=1HOUR
WQ Output Interval=15MIN
WQ Output Selected Increments= 0
WQ Output face flow=0
WQ Output face velocity=0
WQ Output face area=0
WQ Output face dispersion=0
WQ Output cell volume=0
WQ Output cell surface area=0
WQ Output cell continuity=0
WQ Output cumulative cell continuity=0
WQ Output face conc=0
WQ Output face dconc_dx=0
WQ Output face courant=0
WQ Output face peclet=0
WQ Output face adv mass=0
WQ Output face disp mass=0
WQ Output cell mass=0
WQ Output cell source sink temp=0
WQ Output nsm pathways=0
WQ Output nsm derived pathways=0
WQ Create Restart=0
WQ Fixed Restart=0
WQ System Summary=0
WQ Write To DSS=0
Sorting and Armoring Iterations= 10
XS Update Threshold= 0.02
Bed Roughness Predictor= 0
Hydraulics Update Threshold= 0.02
Energy Slope Method= 1
Volume Change Method= 1
Sediment Retention Method= 0
Sediment TS Multiplier= 1
Warm Up Method= 0
XS Weighting Method= 0
Number of US Weighted Cross Sections= 1
Number of DS Weighted Cross Sections= 1
Upstream XS Weight=0
Main XS Weight=1
Downstream XS Weight=0
Number of DS XS's Weighted with US Boundary= 1
Upstream Boundary Weight= 1
Weight of XSs Associated with US Boundary= 0
Number of US XS's Weighted with DS Boundary= 1
Downstream Boundary Weight= 0.5
Weight of XSs Associated with DS Boundary= 0.5
Percentile Method= 0
Sediment Output Level= 3
Mass or Volume Output= 0
Output Increment Type= 1
Profile and TS Output Increment= 1
Transport Output Increment 1
XS Output Flag= 0
XS Output Increment= 10
Read HDF5 Sediment Hotstart= 0
Sediment Hotstart Type= 0
Write Gradation File= 0
Read Gradation Hotstart= 0
Write HDF5 File= 1
Write Binary Output= 1
Write DSS Sediment File= 0
DSS Sediment Output Type= 1
SV Curve= 0
Specific Gage Flag= 0
Subcell Erosion Methods= 0
Subcell Deposition Methods= 0
Advection Scheme= 1
Matrix Solver= 0
Implicit Weighting Factor= 1
Maximum Outer Loop Convergence Iterations= 5
Convergence Maximum Absolute= 0.001
Convergence RMSE= 0.0001
Grain Fractions Max Abs Error= 0.001
Max Subgrid Regions= 1
Max Subgrid Length Scale= 3.402823E+38
Initial Layer Thickness= 3.402823E+38
Min Layer Thickness= 3.402823E+38
Max Layer Thickness= 3.402823E+38
Number of Layers= 5

--- HEWETTFK.f01 (steady flow) ---

Flow Title=Flow
Program Version=6.20
Number of Profiles= 1
Profile Names=P100yr
River Rch & RM=HEWETTFK,Main,10529
     422
River Rch & RM=HEWETTFK,Main,8432
     472
River Rch & RM=HEWETTFK,Main,5649
     563
River Rch & RM=HEWETTFK,Main,2356
     634
Boundary for River Rch & Prof#=HEWETTFK,Main            , 1
Up Type= 0
Dn Type= 3
Dn Slope=0.02641
DSS Import GetInterval= 0
DSS Import GetPeak= 0
DSS Import FillOption= 0

--- HEWETTFK.g01 (geometry) ---

Geom Title=Geometry
Program Version=6.20

River Reach=HEWETTFK        ,Main
Reach XY= 30
2215917.88500002      573129.9122215332.81600001 573172.62000002
     2214406.427572896.2310000062214209.20500001572963.938999996
     2214084.205573211.509000003     2213533.163573789.981000006
2213501.91300002574013.245000005     2213096.531574517.931999996
2212889.06600003575084.7730000172212729.34299999575171.578000009
2212682.03500003575362.1159999972212430.04500002575589.275000021
2212137.84999999575719.5290000142212096.98800001575834.818000004
2211982.62200002575847.9480000142211983.26536814575913.093165536
2211409.58100004576314.802000016     2211015.575576712.664000005
2210671.67500004 576844.870000022210670.13200003577322.386999995
2210465.95800002577473.7000000032210431.88300002577618.651999995
2210210.09000002577625.4740000072210085.86300001577840.397000015
2209797.07599999 577769.363000022209754.12200001577816.130999997
2209762.74700004577949.9310000092209277.81663527577991.241440997
2208969.22284153578478.857096925     2208888.675578470.369000018

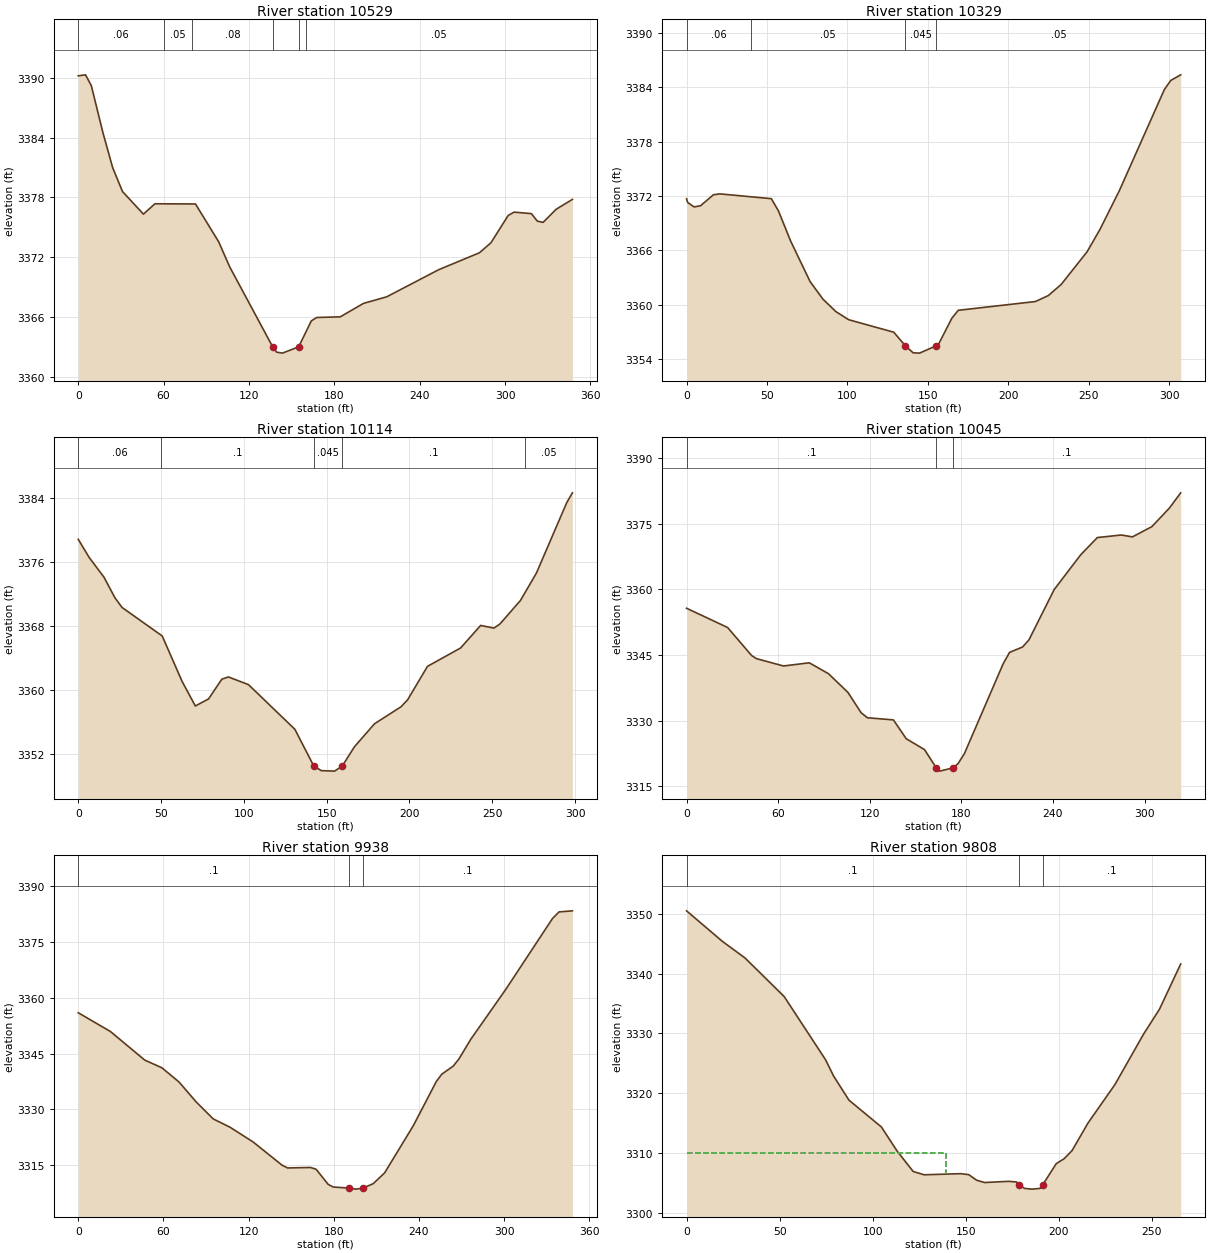
Type RM Length L Ch R = 1 ,10529   ,199,200.4,201.6
XS GIS Cut Line= 2
2215880.86074461572988.1727263232215945.19005734 573329.44141764
#Sta/Elev= 30
       0 3390.22     5.1 3390.32     9.2 3389.23    17.3 3384.53    24.2 3380.99
    31.1 3378.59    45.8 3376.32    53.9 3377.36    82.4 3377.34    98.7 3373.54
   106.4 3371.03  136.673362.979   139.4 3362.45   143.5 3362.35  154.923362.979
   163.8 3365.59   167.6 3365.93   184.2    3366   200.5 3367.35   216.8 3368.01
   253.4 3370.74   281.9 3372.43     290 3373.43   302.2 3376.19   306.3 3376.52
   318.5 3376.37   322.6 3375.62   326.7 3375.49   335.9 3376.81   347.3  3377.8
#Mann= 6, -1 ,  0
       0    0.06       0      60    0.05       0      80    0.08       0
  136.67   0.045       0  154.92    0.08       0     160    0.05       0
Bank Sta=136.67,154.92
XS Rating Curve= 0 ,0
Exp/Cntr=0.3,0.1

Type RM Length L Ch R = 1 ,10329   ,214.3,214.7,214.4
XS GIS Cut Line= 2
2215701.66421072 573008.525352072215717.11368042573315.307679043
#Sta/Elev= 30
       0 3371.68      .7 3371.27     4.7 3370.78     8.7 3370.91    16.7 3372.12
    20.7 3372.22    52.7 3371.69    57.1 3370.35    64.7 3367.01    76.8 3362.53
    84.8 3360.59    92.8 3359.22   100.8 3358.32   128.8 3356.94     1363355.447
   140.8 3354.67   144.8 3354.63  155.283355.445   156.9  3355.7   164.9 3358.48
   168.9 3359.36   216.9 3360.33   224.9 3360.99   232.9 3362.22     249 3365.83
     257  3368.3     269 3372.56     297 3383.74     301 3384.75307.1711 3385.37
#Mann= 4, -1 ,  0
       0    0.06       0      40    0.05       0     136   0.045       0
  155.28    0.05       0
Bank Sta=136,155.28
XS Rating Curve= 0 ,0
Exp/Cntr(USF)=0,0
Exp/Cntr=0.3,0.1

Type RM Length L Ch R = 1 ,10114   ,71.6,69.2,69
XS GIS Cut Line= 2
2215486.47516842572998.5935501172215503.02817167573296.547608689
#Sta/Elev= 30
       0 3378.81     6.6 3376.54    15.5  3374.1    22.1 3371.54    26.4 3370.32
    50.7 3366.76    62.7  3361.1    70.7 3358.03    78.7 3358.91    86.7 3361.37
    90.7 3361.65   102.8 3360.69   130.8 3355.13  142.26 3350.54   146.8 3349.97
   154.8 3349.91  159.433350.541   166.8 3352.95   178.9 3355.81   194.9 3357.93
   198.9  3358.8   210.9 3362.97   230.9 3365.26     243 3368.07     251 3367.74
   254.6 3368.24     267 3371.17   276.7  3374.6     295 3383.38298.4135  3384.6
#Mann= 5, -1 ,  0
       0    0.06       0      50     0.1       0  142.26   0.045       0
  159.43     0.1       0     270    0.05       0
Bank Sta=142.26,159.43
XS Rating Curve= 0 ,0
Exp/Cntr(USF)=0,0
Exp/Cntr=0.3,0.1

Type RM Length L Ch R = 1 ,10045   ,105,106.9,109.6
XS GIS Cut Line= 2
  2215369.966784 572989.146704842215475.74034773573295.093894547
#Sta/Elev= 30
       0 3355.69    26.9 3351.29    42.6  3344.9    45.8 3344.18    63.5 3342.51
    80.4 3343.23      93 3340.74   105.8 3336.44   114.3 3331.85   118.5 3330.68
   135.5  3330.2   143.9  3325.9   155.9 3323.41  163.54 3319.26   165.9  3318.5
  174.78 3319.27   177.9 3320.24     182 3322.49   207.4 3343.01   211.6 3345.61
   220.1 3346.84   224.3 3348.47   240.8 3359.94   258.2  3367.9   269.1 3371.83
   284.8 3372.41   292.1 3371.98   304.8 3374.32   316.3 3378.56   323.7 3382.04
#Mann= 3, -1 ,  0
       0     0.1       0  163.54   0.045       0  174.78     0.1       0
Bank Sta=163.54,174.78
XS Rating Curve= 0 ,0
Exp/Cntr(USF)=0,0
Exp/Cntr=0.3,0.1

Type RM Length L Ch R = 1 ,9938    ,128.6,129.6,131.1
XS GIS Cut Line= 3
2215344.52994795572978.6432762272215314.58920531573241.661184612
2215334.39615814573322.731503134
#Sta/Elev= 30
       0 3355.95    22.7 3350.91    46.8 3343.26    58.9 3341.19      71 3337.38
    83.1 3332.02    95.1 3327.47     107 3325.23   123.3 3321.26   143.6 3315.06
   147.5 3314.31   163.6 3314.44   167.6 3313.97   176.1 3309.91   179.7 3309.19
   190.6 3308.92   195.8 3308.63  200.88 3308.92   207.9 3310.11   215.9    3313
   236.1 3325.65   252.3 3337.49   256.2 3339.48   264.2 3341.62   268.3 3343.58
   276.6 3348.83   301.3 3362.24   334.2 3381.24   338.8    3383   348.2 3383.29
#Mann= 3, -1 ,  0
       0     0.1       0   190.6   0.045       0  200.88     0.1       0
Bank Sta=190.6,200.88
XS Rating Curve= 0 ,0
Exp/Cntr(USF)=0,0
Exp/Cntr=0.3,0.1

Type RM Length L Ch R = 1 ,9808    ,370.1,369.9,368.2
XS GIS Cut Line= 2
2215266.62490687572967.2002533652215173.19733752573215.842589656
#Sta/Elev= 30
       0 3350.46    19.2 3345.38    31.4  3342.6    52.5 3336.15    74.8 3325.57
      79 3322.91    87.3 3318.87   104.7 3314.41   113.2 3310.37   121.8 3306.98
   127.7 3306.42   147.4 3306.61   151.7 3306.44   155.9 3305.52   160.2 3305.13
     173 3305.33   177.3 3305.23  178.933304.784   181.6 3304.15   185.9 3304.03
   190.1 3304.16  191.523304.786   198.7 3308.28   202.9 3309.09   207.2 3310.46
   215.8 3315.07   230.2 3321.45   245.6 3329.87   254.2 3334.05   265.6  3341.6
#Mann= 3, -1 ,  0
       0     0.1       0  178.93   0.045       0  191.52     0.1       0
#XS Ineff= 2 , 0
        139.6404    3310
Permanent Ineff=
       F       F
Bank Sta=178.93,191.52
XS Rating Curve= 0 ,0
Exp/Cntr=0.3,0.1

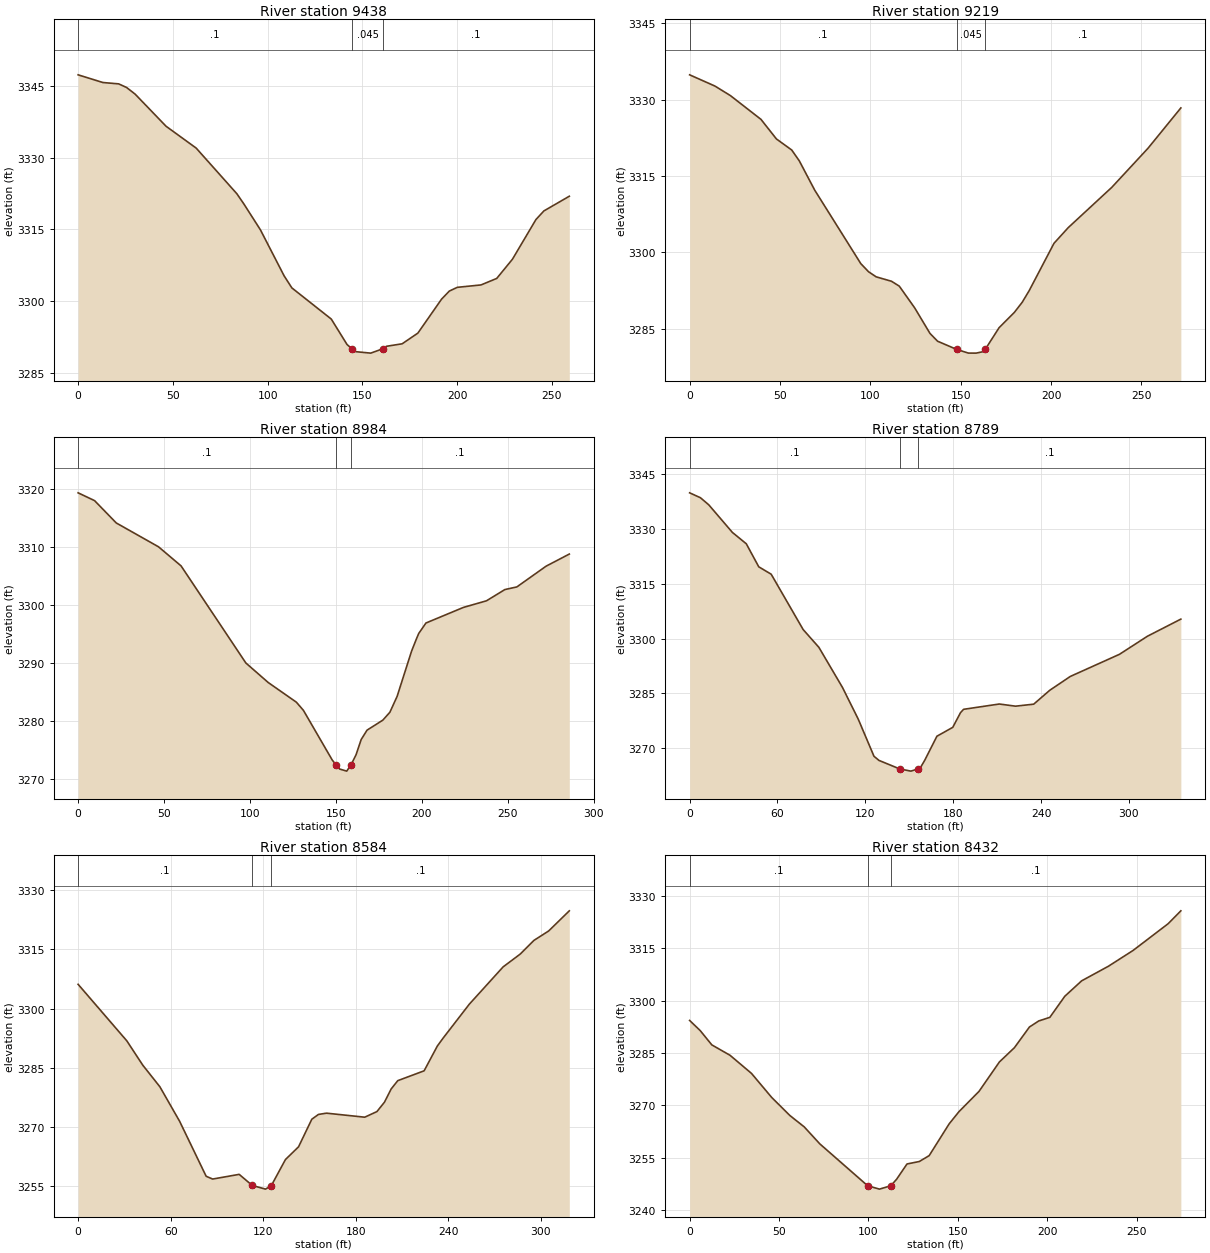
Type RM Length L Ch R = 1 ,9438    ,218.6,219.3,219.7
XS GIS Cut Line= 2
2214908.30775081572864.5464880442214838.21076383573114.095717398
#Sta/Elev= 30
       0 3347.33    13.1 3345.72    21.4 3345.44    25.6 3344.68    30.1 3343.29
    46.4 3336.58    62.3 3332.01    83.8 3322.45    87.4 3320.37    96.2 3314.92
   108.7  3305.3   112.8 3302.77   133.6 3296.25   141.9 3290.94  144.39 3290.07
   146.6 3289.43   154.4 3289.13  160.97 3290.06   162.7 3290.56     171 3291.08
   179.3 3293.32   191.8 3300.42   195.9 3302.11   200.1 3302.89   212.6 3303.39
   220.9 3304.75   229.2 3308.77   241.6 3317.07   245.8 3318.87   259.2 3321.94
#Mann= 3, -1 ,  0
       0     0.1       0  144.39   0.045       0  160.97     0.1       0
Bank Sta=144.39,160.97
XS Rating Curve= 0 ,0
Exp/Cntr=0.3,0.1

Type RM Length L Ch R = 1 ,9219    ,235.5,235.2,234.9
XS GIS Cut Line= 3
2214703.52594592572827.9871960262214632.65996544573025.852687275
2214628.43228142 573087.33233427
#Sta/Elev= 30
       0 3334.89      14 3332.68    22.5 3330.82    39.5 3326.12      48 3322.29
    56.5  3320.1    60.7 3317.96    69.2 3312.22    94.7 3297.77      99 3296.17
   103.2 3295.17   111.7  3294.3     116 3293.34   124.5 3289.08     133 3284.04
   137.2 3282.51   147.73280.913   154.2 3280.18   158.5 3280.17   162.7 3280.48
  163.583280.914   171.2 3285.16   179.7 3288.19     184 3290.16   187.9 3292.47
   201.6 3301.76   209.5 3304.85   233.6 3312.77   253.6 3320.44   271.8 3328.38
#Mann= 3, -1 ,  0
       0     0.1       0   147.7   0.045       0  163.58     0.1       0
Bank Sta=147.7,163.58
XS Rating Curve= 0 ,0
Exp/Cntr=0.3,0.1

Type RM Length L Ch R = 1 ,8984    ,199.6,195,188.6
XS GIS Cut Line= 3
2214473.68970792572756.0321505752214412.27279995572952.054448515
 2214446.5639069573024.731122947
#Sta/Elev= 30
       0 3319.32     9.6 3317.97    22.2 3314.12    46.8    3310    59.9 3306.71
    97.6 3289.95   110.6 3286.58     127 3283.18   131.1 3281.77   147.9 3273.18
  150.11 3272.36   152.2 3271.64   156.3 3271.28   158.83272.365   161.7 3274.09
   164.7 3276.73   168.1 3278.35   177.3 3280.08   181.4 3281.44   185.6 3284.17
     194 3291.97   196.8 3294.07   198.2 3295.05   202.4 3296.85   224.2 3299.54
   237.6 3300.68   248.3 3302.62   255.3 3303.08   272.3 3306.66   285.8 3308.75
#Mann= 3, -1 ,  0
       0     0.1       0  150.11   0.045       0   158.8     0.1       0
Bank Sta=150.11,158.8
XS Rating Curve= 0 ,0
Exp/Cntr(USF)=0,0
Exp/Cntr=0.3,0.1

Type RM Length L Ch R = 1 ,8789    ,207,205.1,201
XS GIS Cut Line= 3
2214147.24303071572827.4642829352214308.98789752573007.726167895
2214387.32180681573058.453117197
#Sta/Elev= 30
       0 3339.88     7.4 3338.53    13.1 3336.58    29.2 3329.04    38.7 3325.93
    47.2 3319.63    55.7  3317.6    77.5 3302.47    88.3 3297.57   104.4  3286.6
   115.2 3277.89   125.9 3267.77   129.3 3266.64   143.5  3264.3   151.1  3263.7
   155.9 3264.29   158.2 3265.05   160.5 3266.62   168.9 3273.26   179.7 3275.68
     185  3279.7   187.1 3280.62   211.5 3282.07   222.6 3281.48     235 3282.03
     246 3285.84     260 3289.62   293.6 3295.68   312.7 3300.63   335.5 3305.31
#Mann= 3, -1 ,  0
       0     0.1       0   143.5   0.045       0   155.9     0.1       0
Bank Sta=143.5,155.9
XS Rating Curve= 0 ,0
Exp/Cntr(USF)=0,0
Exp/Cntr=0.3,0.1

Type RM Length L Ch R = 1 ,8584    ,149.7,151.8,155.2
XS GIS Cut Line= 3
 2214038.7065098573064.4831076732214260.39009857573149.388024889
2214315.81950623573208.408431357
#Sta/Elev= 30
       0 3306.16    31.6 3291.83    41.9 3285.69      53 3280.21    65.8 3271.47
      83 3257.54    87.2 3256.83   104.4 3258.02   112.9 3255.21   121.5 3254.28
  125.28 3255.19   134.4 3261.77   142.9    3265   151.5 3271.99   155.8  3273.2
     161 3273.52   185.8  3272.5   193.7 3273.92   198.6 3276.31   202.9 3279.63
   207.2 3281.75   224.3 3284.25   232.9 3290.55   236.8 3292.63   253.6 3301.13
   275.5 3310.57   286.5 3313.79   295.5 3317.29     305 3319.66   318.4 3324.77
#Mann= 3, -1 ,  0
       0     0.1       0   112.9   0.045       0  125.28     0.1       0
Bank Sta=112.9,125.28
XS Rating Curve= 0 ,0
Exp/Cntr(USF)=0,0
Exp/Cntr=0.3,0.1

Type RM Length L Ch R = 1 ,8432    ,295.6,296.1,296.2
XS GIS Cut Line= 2
2213991.57518626573156.9139817092214182.73894591573354.267639698
#Sta/Elev= 30
       0  3294.3     5.9 3291.41    12.4 3287.32    22.6 3284.34    34.6 3279.16
    45.9 3272.29    56.1 3267.11    64.1 3263.87    72.8 3259.02   99.563247.044
   106.2 3246.07  112.573247.043   115.8 3248.91   121.6 3253.26   128.5 3253.97
     134 3255.65   145.2 3264.75   150.7 3268.24   161.9 3274.03   173.3 3282.44
   181.7 3286.52   190.1 3292.43   195.3 3294.16   201.5 3295.19   209.9 3301.23
   219.3 3305.63   234.3 3309.81   248.1 3314.33   267.7 3321.97   274.8 3325.65
#Mann= 3, -1 ,  0
       0     0.1       0   99.56   0.045       0  112.57     0.1       0
Bank Sta=99.56,112.57
XS Rating Curve= 0 ,0
Exp/Cntr=0.3,0.1

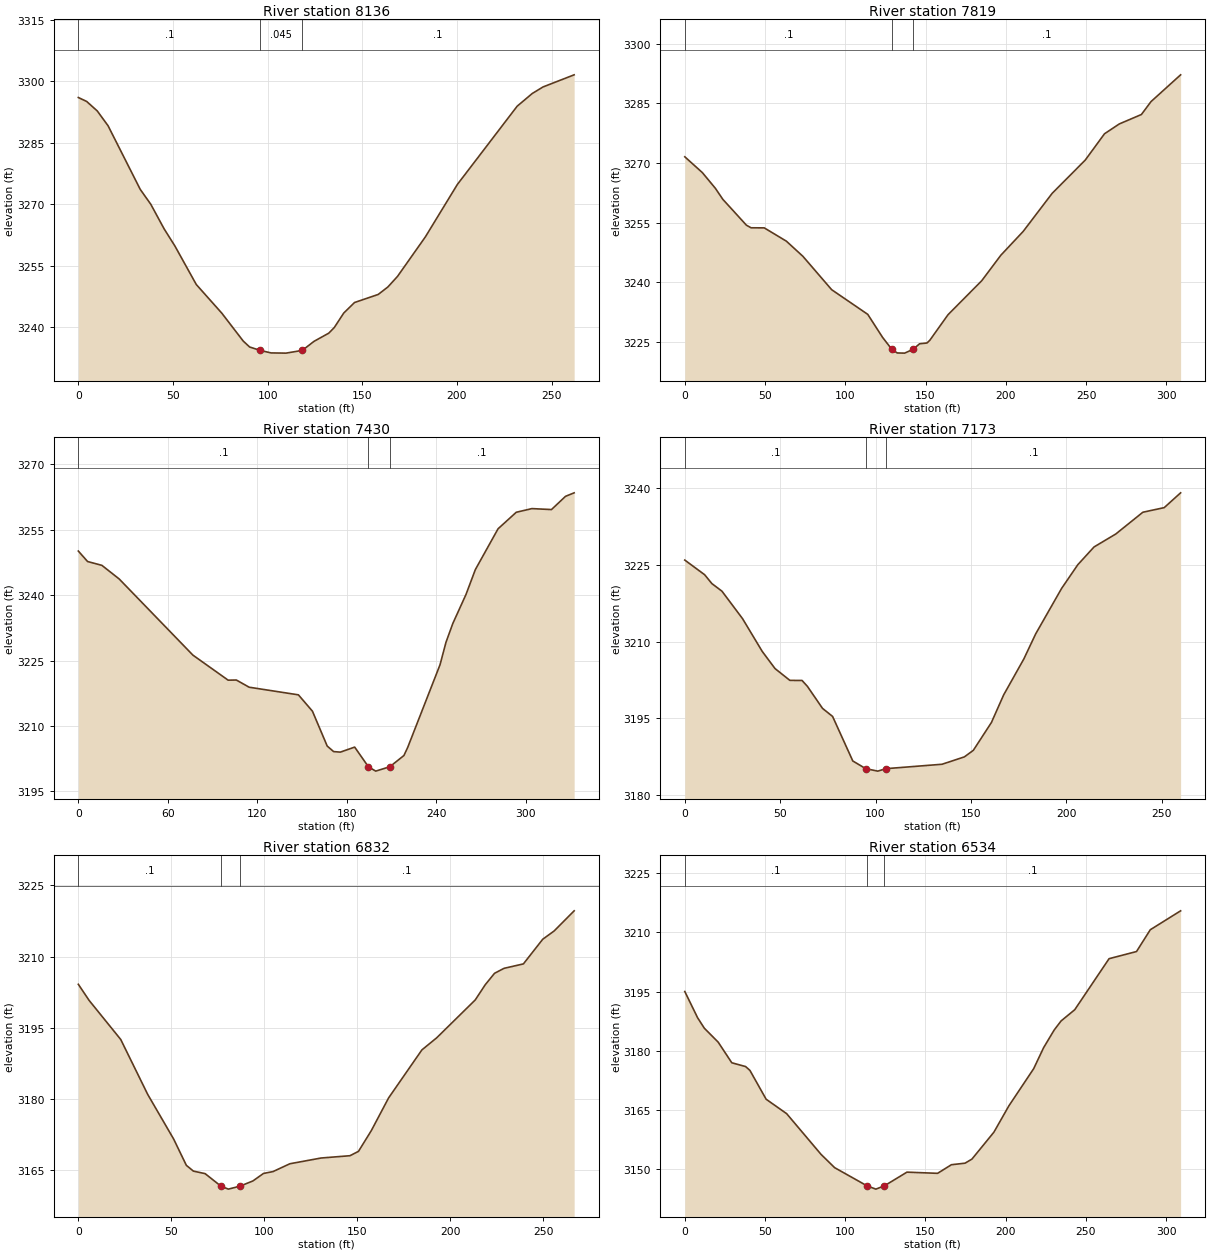
Type RM Length L Ch R = 1 ,8136    ,317.6,316.5,313.7
XS GIS Cut Line= 2
2213793.09626313573373.0978344922213978.14157137573558.478145984
#Sta/Elev= 30
       0 3296.08     4.4 3295.12      10  3292.8    15.7 3289.19    32.7 3273.65
    38.3 3269.99    45.3 3264.02      51 3259.83    62.3 3250.42    75.8 3243.41
    87.1 3236.61    90.5 3235.15   96.123234.325   101.8 3233.71   109.7 3233.66
  118.283234.324   124.5 3236.54   132.3 3238.54   135.2 3239.91   140.2 3243.45
   145.9 3246.02   158.4 3247.99   163.5 3249.81   168.6  3252.4   183.3 3262.04
   200.2 3274.84   231.8 3293.96   239.8 3297.07   245.5 3298.67   261.9 3301.62
#Mann= 3, -1 ,  0
       0     0.1       0   96.12   0.045       0  118.28     0.1       0
Bank Sta=96.12,118.28
XS Rating Curve= 0 ,0
Exp/Cntr=0.3,0.1

Type RM Length L Ch R = 1 ,7819    ,388.4,388.9,388.7
XS GIS Cut Line= 2
2213533.22078445573607.7440698632213801.37943716 573761.13523335
#Sta/Elev= 30
       0 3271.57    10.9 3267.61      19 3263.67    23.7 3260.87    38.4 3254.36
    41.3 3253.71    49.5 3253.69    63.3 3250.34    73.6 3246.53    91.5 3238.14
     114 3231.93   123.2 3226.16     1293223.126   132.4 3222.22     137 3222.18
  142.173223.129   146.3 3224.53   150.9 3224.73   152.7 3225.43     164 3231.84
     185 3240.39   196.9  3246.8   210.8 3252.78   228.9 3262.38   249.5 3270.74
   261.5 3277.36   270.7 3279.83   284.5 3282.21   290.5 3285.46308.9303 3292.19
#Mann= 3, -1 ,  0
       0     0.1       0     129   0.045       0  142.17     0.1       0
Bank Sta=129,142.17
XS Rating Curve= 0 ,0
Exp/Cntr(USF)=0,0
Exp/Cntr=0.3,0.1

Type RM Length L Ch R = 1 ,7430    ,257,257.8,259.4
XS GIS Cut Line= 2
2213338.91665597573896.6537543762213621.10475763 574072.12003254
#Sta/Elev= 30
       0 3250.12     6.2 3247.72    15.8 3246.84    27.4 3243.71    76.8 3226.24
   100.4  3220.5   105.9 3220.53   114.5 3218.88   147.5 3217.13   156.9 3213.38
   166.8 3205.38   171.1 3204.11   175.6 3203.99   185.2 3205.14  194.393200.639
   199.3 3199.63  208.78 3200.64   218.2 3203.21   220.7 3205.03   242.4 3224.03
   246.4 3229.19     251 3233.52   259.8 3240.15   266.1 3245.88   281.3 3255.23
   293.5 3259.02     304 3259.86   317.1 3259.64   326.5 3262.67   332.3 3263.48
#Mann= 3, -1 ,  0
       0     0.1       0  194.39   0.045       0  208.78     0.1       0
Bank Sta=194.39,208.78
XS Rating Curve= 0 ,0
Exp/Cntr=0.3,0.1

Type RM Length L Ch R = 1 ,7173    ,340.8,340.2,340.4
XS GIS Cut Line= 2
2213257.36569262574117.2936127632213454.58694506574286.671864863
#Sta/Elev= 30
       0 3225.93    10.4 3223.07    14.2 3221.34    19.5 3219.85    30.3 3214.48
    40.6  3208.1    47.3 3204.75    55.1 3202.44    61.5 3202.42    64.3 3201.27
    72.2 3196.98    77.5  3195.4    88.1  3186.7    94.93185.199   101.2 3184.72
  105.48  3185.2   134.9 3186.06   146.6  3187.5   151.3 3188.78   160.8 3194.22
   167.2  3199.6   177.8 3206.63     184 3211.52   197.6  3220.4   206.1 3225.03
   214.6 3228.49     226 3231.02   240.2 3235.27   251.4 3236.17     260 3239.06
#Mann= 3, -1 ,  0
       0     0.1       0    94.9   0.045       0  105.48     0.1       0
Bank Sta=94.9,105.48
XS Rating Curve= 0 ,0
Exp/Cntr(USF)=0,0
Exp/Cntr=0.3,0.1

Type RM Length L Ch R = 1 ,6832    ,299.4,298.7,295.9
XS GIS Cut Line= 2
2213083.34630789574397.8590453992213289.25007496574567.357230047
#Sta/Elev= 30
       0 3204.16     5.8 3200.77    22.8 3192.55    37.3    3181    51.3 3171.57
    58.1 3166.06    61.9 3164.84    68.2 3164.31   76.69 3161.68    80.7 3161.05
      87 3161.68    93.9 3162.77    99.6 3164.35   104.7 3164.74   113.8 3166.39
   130.6  3167.6   146.1 3168.08   150.7    3169   157.6 3173.37   166.9 3180.25
   184.8 3190.35   192.8 3192.91   213.5 3200.87   218.9 3204.08   223.9 3206.48
     229 3207.52   239.4 3208.45   249.8 3213.64   255.9 3215.37   266.7 3219.62
#Mann= 3, -1 ,  0
       0     0.1       0   76.69   0.045       0      87     0.1       0
Bank Sta=76.69,87
XS Rating Curve= 0 ,0
Exp/Cntr=0.3,0.1

Type RM Length L Ch R = 1 ,6534    ,314.8,316.6,316.7
XS GIS Cut Line= 2
2212912.73470137574676.2302914752213201.86049154574785.480112951
#Sta/Elev= 30
       0 3195.01       8 3188.35    12.2  3185.7    20.8 3182.19    29.3 3176.96
    37.9    3176    40.6 3175.03    50.7 3167.73    63.5 3164.07    84.9 3153.78
    93.4  3150.4  113.62 3145.79   119.1 3144.96   124.4 3145.79   138.5 3149.26
   157.6 3148.96   166.2 3151.14   174.7 3151.53     179 3152.56   192.7 3159.38
     202 3166.03   217.5 3175.47   223.7 3180.79   230.3 3185.27   234.6 3187.56
   243.1  3190.4   264.5 3203.32   281.6 3205.13   290.2 3210.65   309.1 3215.44
#Mann= 3, -1 ,  0
       0     0.1       0  113.62   0.045       0   124.4     0.1       0
Bank Sta=113.62,124.4
XS Rating Curve= 0 ,0
Exp/Cntr(USF)=0,0
Exp/Cntr=0.3,0.1

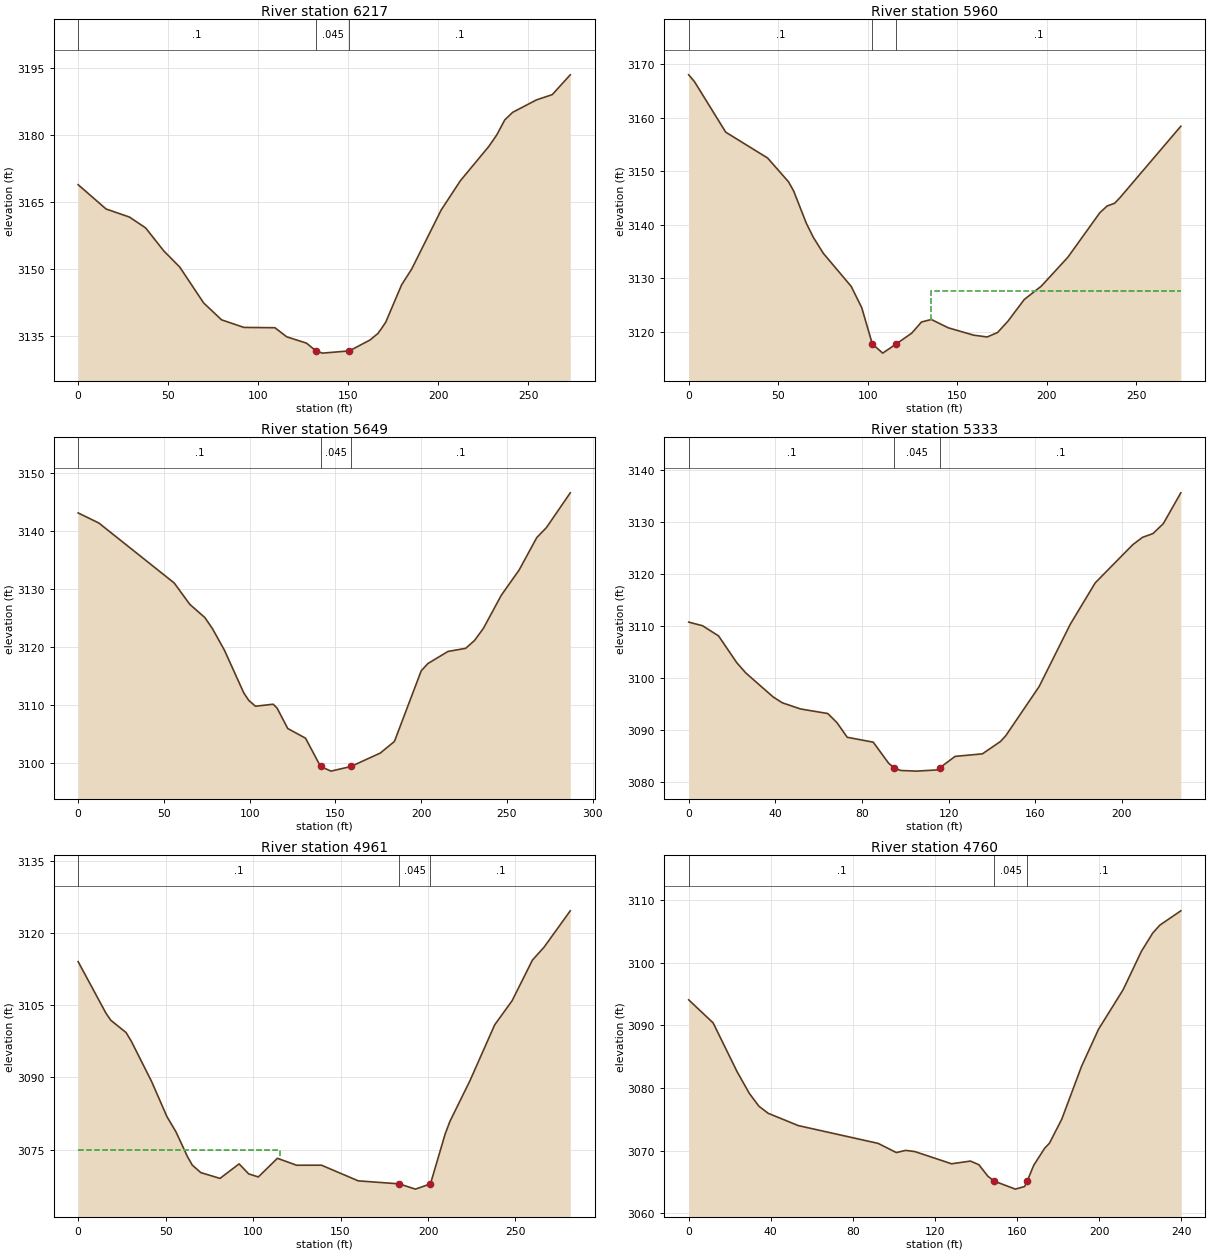
Type RM Length L Ch R = 1 ,6217    ,252.1,257.4,260
XS GIS Cut Line= 2
2212788.89540399574950.6888944352213037.27930435575064.971613017
#Sta/Elev= 30
       0 3168.86    15.5 3163.42    28.5 3161.61    37.5 3159.18    47.6 3154.02
    56.4 3150.44    69.7 3142.39    79.7 3138.59    92.1  3136.9   109.3 3136.83
   115.9 3134.79   126.9 3133.37   132.1 3131.65   135.7 3131.14  150.68 3131.64
   162.1 3134.07   166.5 3135.52   168.6 3136.69   170.9 3138.08   179.7 3146.43
   185.3 3149.96   201.7  3163.2   212.4 3169.77   228.2 3177.45   232.6 3180.02
     237 3183.36   241.4 3185.06   254.6 3187.84   263.4 3189.03   273.4 3193.46
#Mann= 3, -1 ,  0
       0     0.1       0   132.1   0.045       0  150.68     0.1       0
Bank Sta=132.1,150.68
XS Rating Curve= 0 ,0
Exp/Cntr=0.3,0.1

Type RM Length L Ch R = 1 ,5960    ,310.1,310.2,313
XS GIS Cut Line= 3
2212661.97307545575082.3922321982212796.94730481575226.036260251
2212871.65385339575248.060265526
#Sta/Elev= 30
       0 3168.05     3.2 3166.79    20.7 3157.33    44.1  3152.5    55.8 3148.05
    58.7  3146.3    65.8 3140.25    69.7 3137.65    75.2  3134.7    90.8 3128.51
    96.7 3124.53   102.6 3117.76   108.4 3116.03  116.05 3117.76   124.6 3119.76
   130.1 3121.85   135.6 3122.32     145 3120.77   159.2 3119.39   166.8 3119.05
   172.6 3119.88   178.5 3122.04   187.5 3126.05   197.1 3128.57   211.9 3133.96
   229.7 3142.25   233.8 3143.53     238 3144.04   240.9 3145.05     275 3158.44
#Mann= 3, -1 ,  0
       0     0.1       0   102.6   0.045       0  116.05     0.1       0
#XS Ineff= 2 , 0
                          135.33         3127.71
Permanent Ineff=
       F       F
Bank Sta=102.6,116.05
XS Rating Curve= 0 ,0
Exp/Cntr=0.3,0.1

Type RM Length L Ch R = 1 ,5649    ,310.6,316.9,318.7
XS GIS Cut Line= 3
2212520.59072632575290.108425381 2212546.1485368575347.160168762
 2212689.0176185575520.167712471
#Sta/Elev= 30
       0 3143.11    12.1 3141.36      56 3131.01    65.1 3127.32    73.9 3125.03
    78.3 3123.12    85.3 3119.39    96.6    3112    99.5 3110.72   103.4 3109.72
   113.7 3110.07     116 3109.39   122.2 3105.87   132.6 3104.19  141.313099.318
   147.4 3098.51  159.063099.316   176.2 3101.64   184.4 3103.64     200 3115.83
   203.9 3117.09   215.6 3119.18   225.9 3119.72   231.1 3121.08   236.3 3123.19
   246.7 3128.89   257.1 3133.25   267.4 3138.86     273 3140.57   286.9 3146.58
#Mann= 3, -1 ,  0
       0     0.1       0  141.31   0.045       0  159.06     0.1       0
Bank Sta=141.31,159.06
XS Rating Curve= 0 ,0
Exp/Cntr=0.3,0.1

Type RM Length L Ch R = 1 ,5333    ,376.3,371.8,367.8
XS GIS Cut Line= 3
2212333.25052475575508.0385232782212380.86840461575656.878082408
2212420.19834034575715.872986005
#Sta/Elev= 30
       0 3110.76     6.4 3110.06    13.8  3108.1    22.2 3102.94    26.4 3100.95
      39 3096.34    43.2 3095.22    51.6 3094.03    64.2 3093.15    68.4 3091.42
    73.2 3088.57    85.2 3087.63    92.3 3083.58   94.77 3082.71    97.8 3082.18
   105.1 3082.05   114.6 3082.28   115.9 3082.69     123 3084.89   135.6 3085.38
     144 3087.78   146.4 3088.88   161.8 3098.35   176.2 3110.37   187.7 3118.33
     205 3125.67   209.5 3127.09   214.3 3127.81   219.1 3129.72   227.2 3135.67
#Mann= 3, -1 ,  0
       0     0.1       0   94.77   0.045       0   115.9     0.1       0
Bank Sta=94.77,115.9
XS Rating Curve= 0 ,0
Exp/Cntr(USF)=0,0
Exp/Cntr=0.3,0.1

Type RM Length L Ch R = 1 ,4961    ,195.4,201,201.3
XS GIS Cut Line= 3
2211986.69981648 575677.060373972212021.40189126 575735.75402685
2212166.90955749575891.494464181
#Sta/Elev= 30
       0 3114.05    15.8 3103.41    18.7 3101.87    27.4 3099.33    30.4 3097.52
      42 3089.16    50.8 3081.84    55.9 3078.73    62.5 3073.57    65.2 3071.83
    70.1 3070.25    81.1 3069.05      92 3072.06    97.5 3069.98     103 3069.35
   113.9 3073.22   124.9 3071.78   139.1 3071.79   160.1 3068.54  183.493067.914
   192.8 3066.82  201.393067.911   209.8 3078.27   212.5 3080.87     224 3089.36
   238.1 3100.93     248  3105.9   259.7 3114.38   266.4 3117.09   281.3  3124.6
#Mann= 3, -1 ,  0
       0     0.1       0  183.49   0.045       0  201.39     0.1       0
#XS Ineff= 2 , 0
        115.4321    3075
Permanent Ineff=
       F       F
Bank Sta=183.49,201.39
XS Rating Curve= 0 ,0
Exp/Cntr=0.3,0.1

Type RM Length L Ch R = 1 ,4760    ,98.5,97.2,96.9
XS GIS Cut Line= 2
2211911.27931384575770.4852096692212017.63116222575985.421916844
#Sta/Elev= 30
       0 3094.09    11.9 3090.41    23.6  3082.6    29.5 3079.17    34.2  3077.1
    38.7 3075.97    53.4    3074    92.3 3071.16   101.2 3069.69   105.7 3070.04
   110.2 3069.85   128.1  3067.9   137.3 3068.33   141.4 3067.75   145.8 3065.91
   148.93065.126   159.2 3063.85   163.7 3064.27     165 3065.17   168.1 3067.64
   173.4 3070.36   175.8 3071.19   181.8 3075.03   191.4 3083.44   199.7 3089.39
   211.7 3095.71   220.6 3101.84   226.1 3104.75   229.6 3106.03   239.8 3108.31
#Mann= 3, -1 ,  0
       0     0.1       0   148.9   0.045       0     165     0.1       0
Bank Sta=148.9,165
XS Rating Curve= 0 ,0
Exp/Cntr(USF)=0,0
Exp/Cntr=0.3,0.1

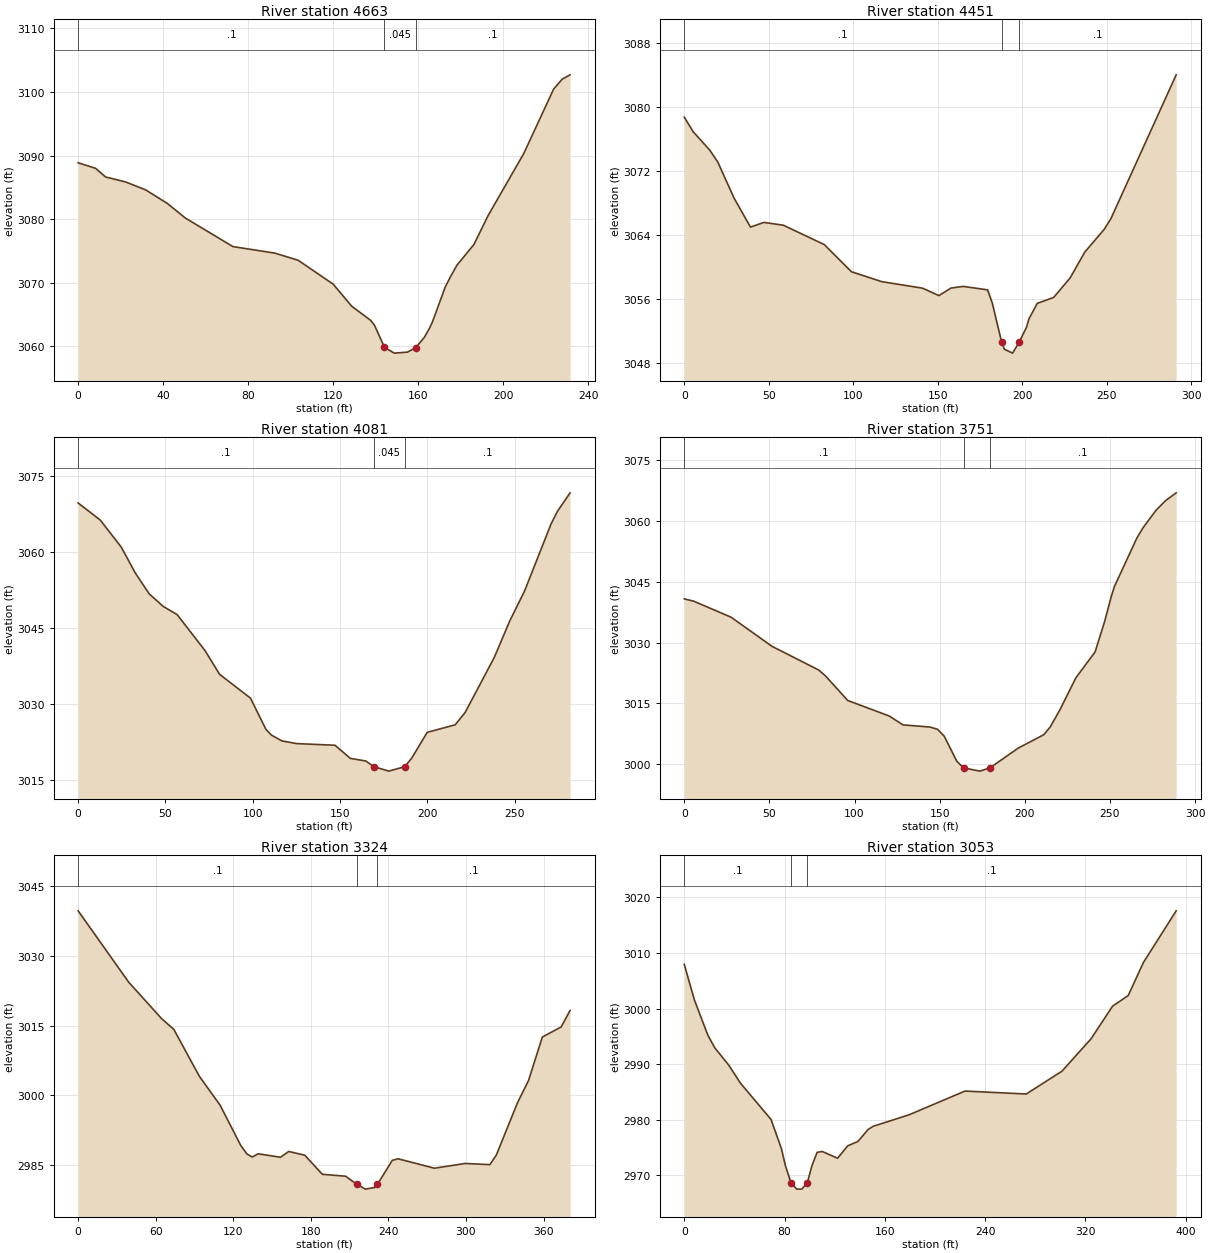
Type RM Length L Ch R = 1 ,4663    ,213.3,211.2,209.2
XS GIS Cut Line= 2
2211822.31244061575838.1479589032211942.67509938576035.753733991
#Sta/Elev= 30
       0 3088.86     8.2 3087.99    12.9 3086.63    22.3 3085.85    31.7 3084.61
      42 3082.46    50.4 3080.18    72.8 3075.68    92.5 3074.66   103.5 3073.53
     120 3069.77   128.7  3066.3   137.5 3064.11   139.4 3063.32   144.1 3059.84
   148.7 3058.93   154.9 3059.09  158.79 3059.79   162.8 3061.39   165.1 3062.73
   166.6 3063.78   172.7 3069.34   175.3 3071.03   178.2 3072.76   186.2 3076.02
   192.8 3080.53   209.6  3090.3   223.7 3100.46   227.7 3102.01   231.4 3102.69
#Mann= 3, -1 ,  0
       0     0.1       0   144.1   0.045       0  158.79     0.1       0
Bank Sta=144.1,158.79
XS Rating Curve= 0 ,0
Exp/Cntr(USF)=0,0
Exp/Cntr=0.3,0.1

Type RM Length L Ch R = 1 ,4451    ,366,370.2,373.4
XS GIS Cut Line= 2
2211559.80129277575960.0837026512211800.04230008576124.491364127
#Sta/Elev= 30
       0 3078.71     5.3 3076.88      15 3074.61    19.8 3073.11    29.5 3068.57
    39.2 3064.95    47.1 3065.54    58.6 3065.19    82.9 3062.76    98.9 3059.37
   116.8 3058.13     141 3057.31   150.7 3056.38   157.8 3057.32   165.1 3057.53
   179.5  3057.1   182.3 3055.43  187.773050.593   189.5 3049.66   194.3 3049.18
  198.28 3050.59   202.5 3052.41     204 3053.48   208.9 3055.41   218.6 3056.15
   228.3 3058.58     237 3061.82   248.5 3064.67   252.5 3066.02   291.1 3084.01
#Mann= 3, -1 ,  0
       0     0.1       0  187.77   0.045       0  198.28     0.1       0
Bank Sta=187.77,198.28
XS Rating Curve= 0 ,0
Exp/Cntr=0.3,0.1

Type RM Length L Ch R = 1 ,4081    ,333.3,330,327.2
XS GIS Cut Line= 4
2211393.46803655  576128.46804192211391.58867115576206.094975238
2211447.66751516576327.973472747 2211501.8314245576372.092061875
#Sta/Elev= 30
       0 3069.64    12.7 3066.26    24.7 3060.94    32.7 3055.85    40.7 3051.72
    48.7 3049.25    56.7 3047.63    72.7 3040.52      81 3035.86    98.7 3031.16
   107.5 3025.03   110.6 3023.89   116.6 3022.74   125.1  3022.2   147.1 3021.87
   155.9 3019.28   164.7 3018.77  169.293017.651   177.9 3016.77  187.053017.652
   191.1 3019.37   199.9 3024.42   215.9  3025.9   221.6 3028.32   238.3 3039.18
   247.1 3046.33   255.7 3052.32   270.7  3065.4   274.4 3067.95   281.7 3071.64
#Mann= 3, -1 ,  0
       0     0.1       0  169.29   0.045       0  187.05     0.1       0
Bank Sta=169.29,187.05
XS Rating Curve= 0 ,0
Exp/Cntr=0.3,0.1

Type RM Length L Ch R = 1 ,3751    ,424.3,426.7,429
XS GIS Cut Line= 3
2211133.49061392576383.6872641072211151.39093794576478.560447129
2211287.03993196 576614.91792703
#Sta/Elev= 30
       0 3040.79     5.6 3040.22    27.5 3036.27    51.5 3029.09    78.9 3023.25
    82.9  3021.8      96 3015.72   120.3  3011.9   128.5 3009.69   144.2 3009.17
   148.7 3008.62   152.7 3006.89     160 3000.76     164 2999.08   173.6 2998.28
  179.47 2999.07   196.2 3003.98   211.1 3007.26   214.9 3009.16   220.6 3013.39
     230 3021.31   241.3 3027.72   246.9 3035.24   250.8 3041.42   252.6 3043.82
   265.8  3055.8   269.5 3058.39   277.1 3062.69   282.8 3065.09   288.9 3066.97
#Mann= 3, -1 ,  0
       0     0.1       0     164   0.045       0  179.47     0.1       0
Bank Sta=164,179.47
XS Rating Curve= 0 ,0
Exp/Cntr=0.3,0.1

Type RM Length L Ch R = 1 ,3324    ,274.9,271.2,263.2
XS GIS Cut Line= 4
2210734.02550158576620.0798541762210822.41853895  576698.5410896
2210913.79111691576873.3408039622210965.08388923576913.414539294
#Sta/Elev= 30
       0 3039.68    39.1 3024.33    64.6 3016.47      74 3014.17    93.8 3004.06
   109.8 2997.87   125.7 2989.24   130.6 2987.34   134.7  2986.7   139.3  2987.4
   156.5 2986.65   162.9 2987.89   175.3 2987.09   188.9 2982.98   206.9 2982.57
  215.562980.826   222.2 2979.79   229.5 2980.15  231.562980.827     243 2985.98
   247.5 2986.32   275.6 2984.29   299.3 2985.31   318.5 2985.06   323.5 2987.12
   339.8 2998.34   348.4 3003.16   359.1 3012.53   373.6 3014.68380.5244 3018.23
#Mann= 3, -1 ,  0
       0     0.1       0  215.56   0.045       0  231.56     0.1       0
Bank Sta=215.56,231.56
XS Rating Curve= 0 ,0
Exp/Cntr(USF)=0,0
Exp/Cntr=0.3,0.1

Type RM Length L Ch R = 1 ,3053    ,273.1,272,269.5
XS GIS Cut Line= 3
2210582.81556095576843.031620209 2210632.7409568576892.043197214
2210949.79614984576950.673448097
#Sta/Elev= 30
       0 3007.95     8.1 3001.55    18.7 2995.27    24.3 2992.95    35.5 2989.82
    44.9 2986.56    69.2 2980.06    77.5  2974.8    80.7 2971.71   85.162968.675
    89.7 2967.52    93.8 2967.53   98.132968.669   101.9 2971.77     106 2974.14
   110.1 2974.29   122.3 2973.08   130.4 2975.31   138.5 2976.09   146.7 2978.26
   150.7 2978.82   179.2 2980.88     224 2985.16   272.8 2984.63   301.3 2988.74
   324.5 2994.56   341.7 3000.44   354.1 3002.33   366.3  3008.3   392.4 3017.58
#Mann= 3, -1 ,  0
       0     0.1       0   85.16   0.045       0   98.13     0.1       0
Bank Sta=85.16,98.13
XS Rating Curve= 0 ,0
Exp/Cntr=0.3,0.1