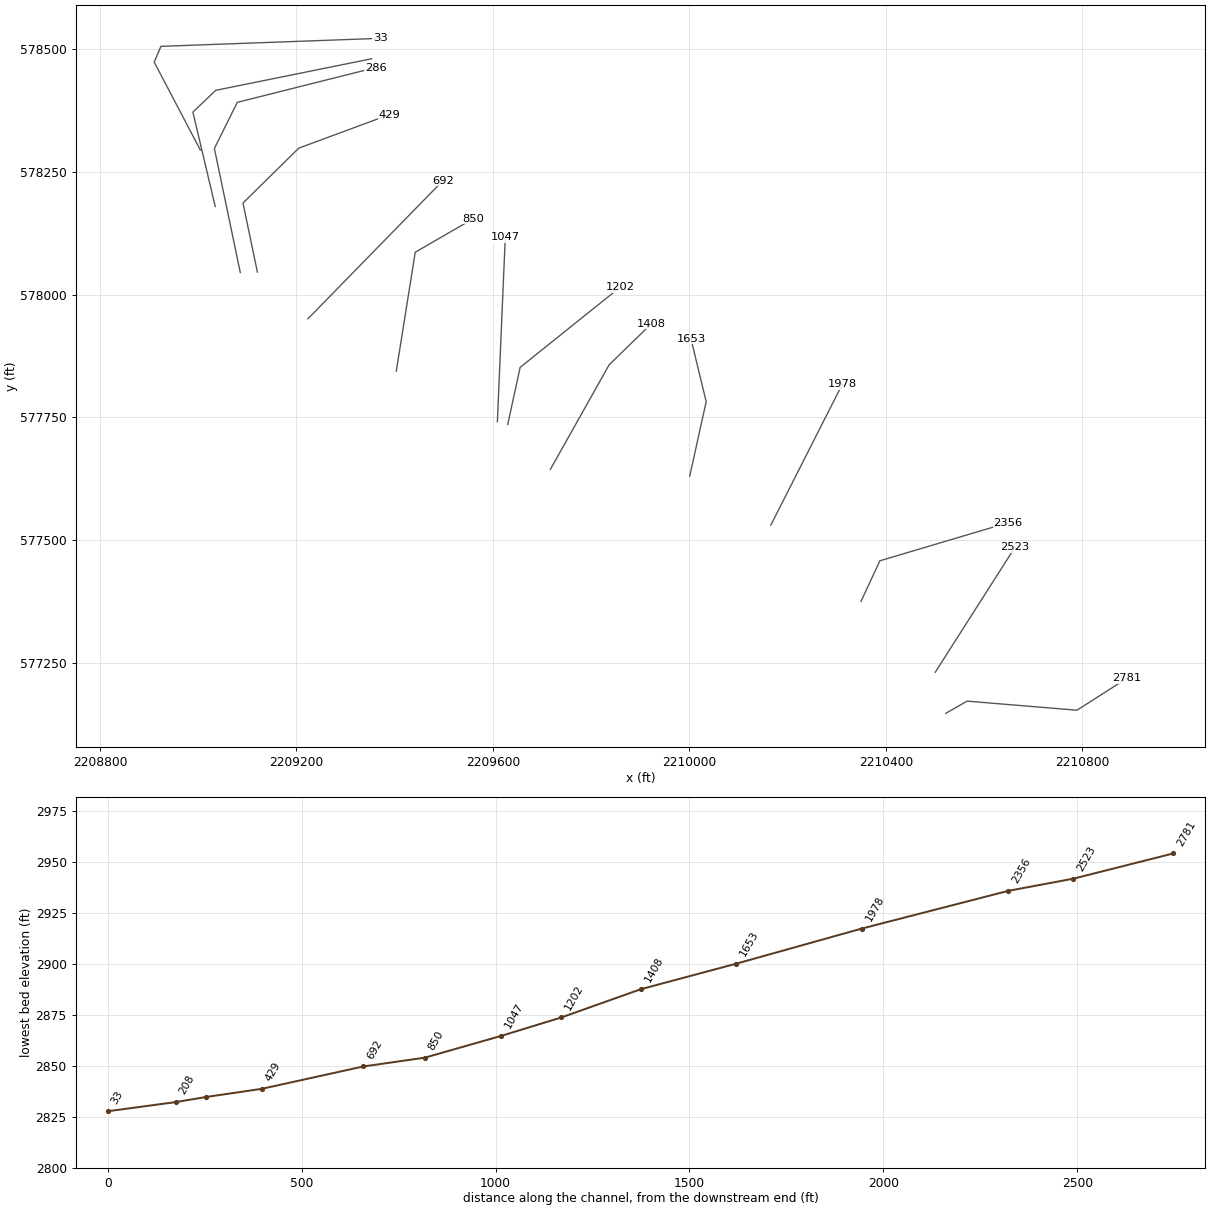
HEC-RAS study HEWETTFK.prj: HEWETTFK

--- HEWETTFK.g01 (geometry) --- (continued)

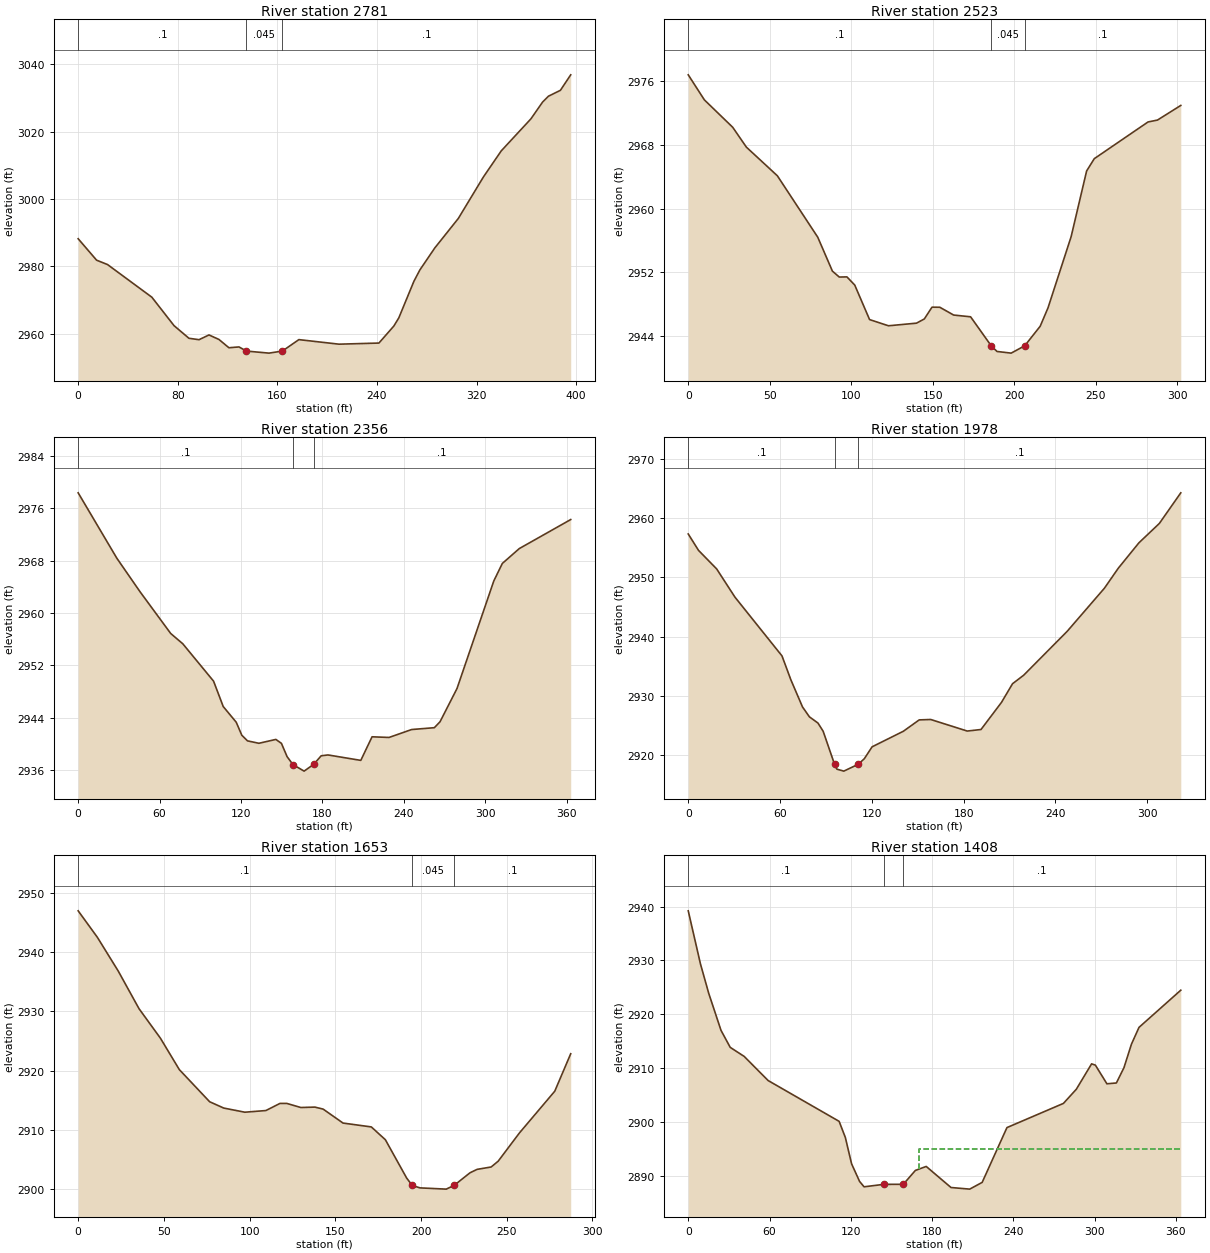
Type RM Length L Ch R = 1 ,2781    ,250.7,258.2,274.9
XS GIS Cut Line= 4
2210521.91656002 577147.241382972210565.35826176577172.180137672
2210789.00257812577153.677190635 2210891.1710248577218.839743245
#Sta/Elev= 30
       0 2988.21    14.8 2981.84    23.6 2980.54    59.2 2970.84      77  2962.4
      89 2958.64    97.1 2958.22   105.1 2959.63   113.1 2958.29   121.1 2955.83
   129.2 2956.07  135.152954.839   153.3 2954.23  164.03 2954.84   177.3 2958.24
   209.5 2956.89   241.6 2957.22   253.6 2962.28   257.6 2964.71   269.7 2975.56
   274.5 2978.94   286.5 2985.48   305.4 2994.24   325.6 3006.59   339.9 3014.32
   363.7 3023.82   373.1 3028.81   377.8 3030.55   387.4  3032.3395.6794  3036.9
#Mann= 3, -1 ,  0
       0     0.1       0  135.15   0.045       0  164.03     0.1       0
Bank Sta=135.15,164.03
XS Rating Curve= 0 ,0
Exp/Cntr(USF)=0,0
Exp/Cntr=0.3,0.1

Type RM Length L Ch R = 1 ,2523    ,174.8,167.4,164.6
XS GIS Cut Line= 2
2210500.58203935577231.0419177732210663.14320493577485.909867168
#Sta/Elev= 30
       0 2976.83     9.9 2973.68    27.3 2970.23    35.7 2967.73    54.7 2964.13
    79.5  2956.4    88.5 2952.13    92.7 2951.39    97.4 2951.41   102.2 2950.38
   111.3 2946.04   122.9 2945.26   140.1 2945.59   144.9 2946.12   149.6  2947.6
   154.4 2947.59   162.9 2946.61   173.3 2946.39     1862942.729   189.5 2942.03
   198.2 2941.82   206.5 2942.74     216  2945.2   220.8 2947.51     235 2956.47
   244.5 2964.73   249.2 2966.28   282.2  2970.9     288 2971.14   302.3 2972.98
#Mann= 3, -1 ,  0
       0     0.1       0     186   0.045       0   206.5     0.1       0
Bank Sta=186,206.5
XS Rating Curve= 0 ,0
Exp/Cntr=0.3,0.1

Type RM Length L Ch R = 1 ,2356    ,368.7,377.8,381.3
XS GIS Cut Line= 3
 2210349.3938598577375.3241112722210387.83941243577457.888539098
2210648.48175665577535.295390657
#Sta/Elev= 30
       0 2978.34    28.5 2968.36    45.6 2963.24    68.2 2956.87    77.1  2955.3
    99.8 2949.59   106.9 2945.72   116.5 2943.32   120.6 2941.34   124.8 2940.48
   133.2 2940.11   145.7  2940.7   149.8  2940.1     154 2938.06   158.3 2936.86
   166.5 2935.86  173.48 2936.88   179.1  2938.2   184.1 2938.33   208.3  2937.5
   216.6  2941.1   229.1    2941   245.8 2942.21   262.5 2942.49   266.7  2943.4
   279.2 2948.47   306.3 2964.88   312.6 2967.56   325.1 2969.83     363 2974.26
#Mann= 3, -1 ,  0
       0     0.1       0   158.3   0.045       0  173.48     0.1       0
Bank Sta=158.3,173.48
XS Rating Curve= 0 ,0
Exp/Cntr(USF)=0,0
Exp/Cntr=0.3,0.1

Type RM Length L Ch R = 1 ,1978    ,305.9,324.6,328.4
XS GIS Cut Line= 2
2210165.79060997577530.5248191612210311.54668885577817.679571072
#Sta/Elev= 30
       0 2957.34     6.7 2954.58    18.6 2951.44    30.5  2946.7    61.3 2936.77
    67.1 2932.74    74.7 2928.17    79.2  2926.5    84.8 2925.45    88.2 2924.07
   95.65 2918.49    97.2 2917.67   101.7 2917.34   111.1 2918.49   115.1 2919.43
   120.2 2921.44   140.6 2924.06     151 2925.98   158.5 2926.05   182.4  2924.1
   191.4 2924.36   204.8 2928.94     212 2932.08   219.3 2933.52   247.7 2940.91
   272.1  2948.2   281.1 2951.55   294.6 2955.84     308 2959.12     322 2964.28
#Mann= 3, -1 ,  0
       0     0.1       0   95.65   0.045       0   111.1     0.1       0
Bank Sta=95.65,111.1
XS Rating Curve= 0 ,0
Exp/Cntr=0.3,0.1

Type RM Length L Ch R = 1 ,1653    ,247.9,245.7,237.4
XS GIS Cut Line= 3
2210000.71265478577630.2903557852210034.16173648577781.846355944
2210003.14024787577910.214877783
#Sta/Elev= 30
       0 2946.95    11.2 2942.49    23.4 2936.79    35.5 2930.46      48 2925.48
      59  2920.2    76.7 2914.78    84.9 2913.72    97.2 2913.02   109.5  2913.3
   117.7  2914.5   121.7  2914.5   129.9 2913.81   138.1 2913.88   142.9 2913.54
   154.5 2911.19     171 2910.54   179.2 2908.38   191.6 2901.93  194.86 2900.68
   199.4 2900.27   214.7 2900.06   219.3 2900.69   228.6 2902.82   232.7 2903.39
   240.9 2903.79     245 2904.77   257.4 2909.53     278 2916.56   287.3 2922.87
#Mann= 3, -1 ,  0
       0     0.1       0  194.86   0.045       0   219.3     0.1       0
Bank Sta=194.86,219.3
XS Rating Curve= 0 ,0
Exp/Cntr=0.3,0.1

Type RM Length L Ch R = 1 ,1408    ,199.2,205.1,194.9
XS GIS Cut Line= 3
2209717.00953241577644.042875322  2209836.647979577856.928934696
2209922.27157313577940.206676931
#Sta/Elev= 30
       0  2939.2       9 2929.37    15.1 2923.91    24.2 2917.01      31 2913.86
    41.3 2912.18      59  2907.7   111.4 2900.13     116 2897.13   120.6 2892.25
   126.5 2888.98   129.8 2887.98   144.2 2888.43   158.8 2888.45   167.7 2891.02
   175.7 2891.76     194 2887.85   207.8 2887.55     217  2888.8   235.3 2898.97
     277 2903.46   286.5 2906.08   297.8  2910.8   300.6 2910.56   309.1  2907.1
   316.1 2907.25   321.7  2910.1   327.2 2914.44   332.8 2917.57363.6432 2924.47
#Mann= 3, -1 ,  0
       0     0.1       0   144.2   0.045       0   158.8     0.1       0
#XS Ineff= 2 , 0
                        170.6353            2895
Permanent Ineff=
       F       F
Bank Sta=144.2,158.8
XS Rating Curve= 0 ,0
Exp/Cntr(USF)=0,0
Exp/Cntr=0.3,0.1

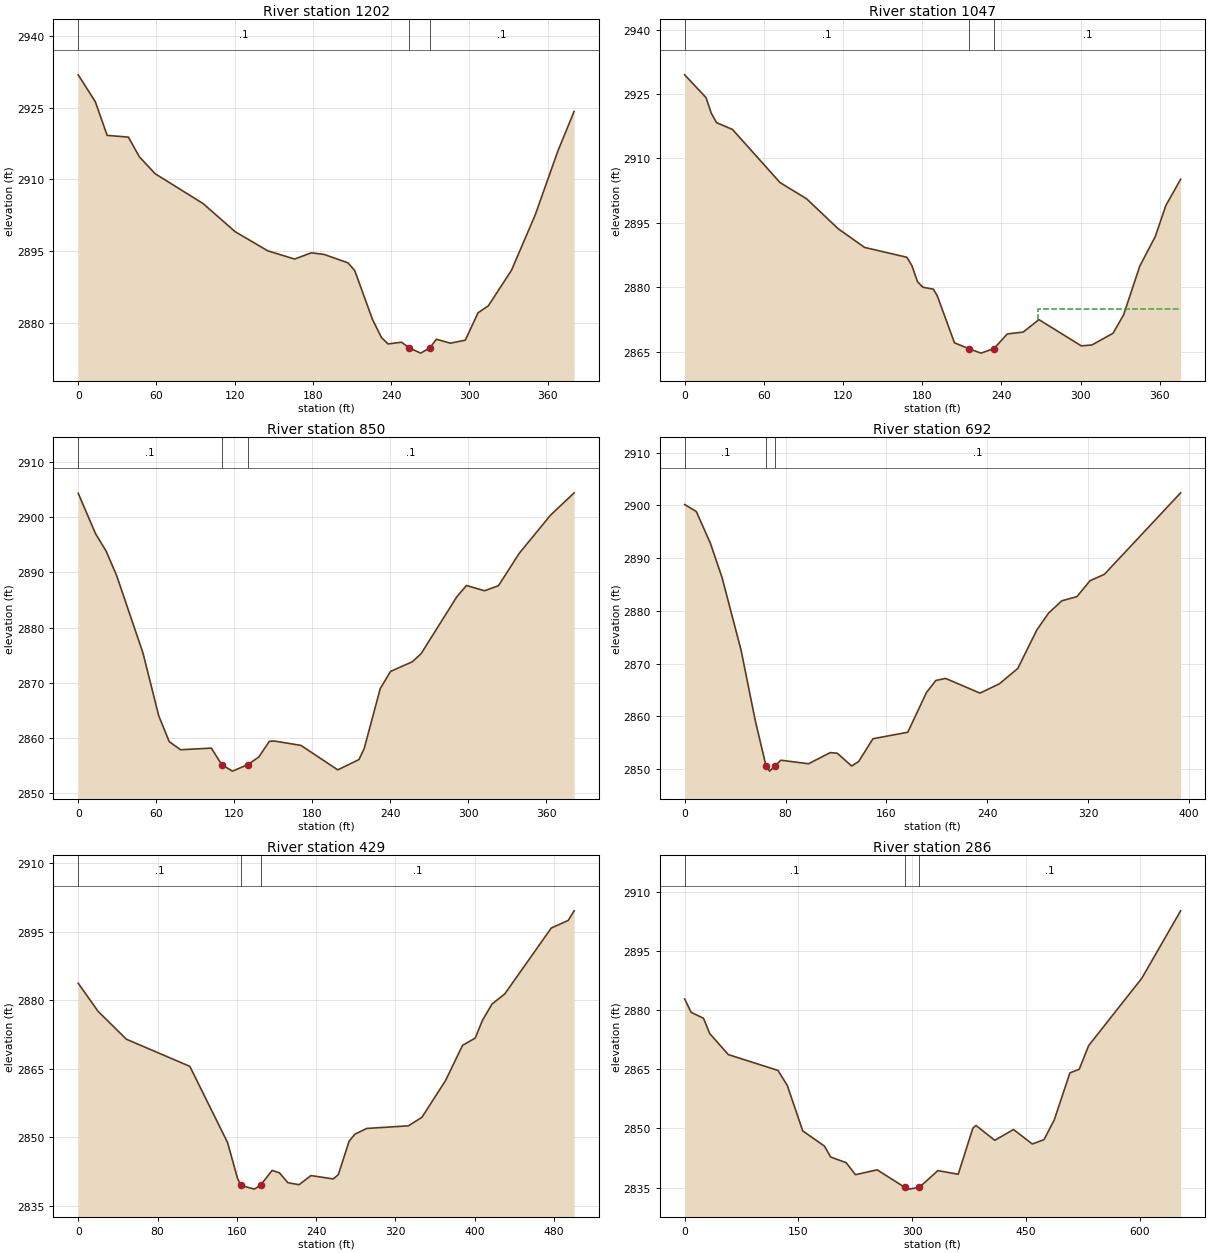
Type RM Length L Ch R = 1 ,1202    ,144.5,155,158.4
XS GIS Cut Line= 3
2209630.21301233577735.5310991852209655.43092019577851.650767935
2209859.52003497578015.273937537
#Sta/Elev= 30
       0 2931.88    13.1 2926.27    22.2 2919.22    38.5 2918.85    46.9 2914.74
      59  2911.2    95.8 2904.95   120.4 2899.07   145.4 2895.07     166 2893.35
   178.8 2894.65   188.7 2894.31   206.9 2892.56   212.1 2890.95   225.7 2880.74
   232.6 2876.93   237.7 2875.59     248 2875.96  253.932874.764   262.7 2873.67
  269.752874.764   274.7 2876.57   285.5 2875.75   296.9 2876.38   306.7 2882.11
   314.6 2883.57   332.3 2890.98   350.5 2902.55     368    2916 380.408 2924.24
#Mann= 3, -1 ,  0
       0     0.1       0  253.93   0.045       0  269.75     0.1       0
Bank Sta=253.93,269.75
XS Rating Curve= 0 ,0
Exp/Cntr(USF)=0,0
Exp/Cntr=0.3,0.1

Type RM Length L Ch R = 1 ,1047    ,198.1,197,195.7
XS GIS Cut Line= 2
2209609.09046762 577740.99054048 2209625.1737658578116.312636083
#Sta/Elev= 30
       0 2929.45    16.2 2924.14    20.2 2920.47    24.2  2918.3    36.2 2916.73
    72.3 2904.34    92.3 2900.59   116.3  2893.6   136.3 2889.25   168.3 2886.96
   172.1 2885.04   176.4 2881.27   180.4 2879.98   188.4 2879.52   191.3 2878.03
   204.4 2867.03  215.15 2865.68   224.4 2864.63   234.32865.681   244.4  2869.1
   256.4 2869.53   268.4 2872.43   300.5 2866.32   308.5 2866.53   324.5 2869.26
   332.5 2873.54   344.8 2884.92   356.5 2891.78   364.5 2899.01   375.7 2905.12
#Mann= 3, -1 ,  0
       0     0.1       0  215.15   0.045       0   234.3     0.1       0
#XS Ineff= 2 , 0
                        267.5921            2875
Permanent Ineff=
       F       F
Bank Sta=215.15,234.3
XS Rating Curve= 0 ,0
Exp/Cntr=0.3,0.1

Type RM Length L Ch R = 1 ,850     ,160.5,158.6,155.7
XS GIS Cut Line= 3
2209403.25184159 577844.026749282209441.91299963 578086.14061537
2209559.83745551578154.265662253
#Sta/Elev= 30
       0 2904.38    13.3 2897.04    21.4  2893.9    29.5 2889.47    49.8 2875.38
    61.9    2864      70 2859.29    78.7 2857.81   102.4 2858.11  110.44 2855.09
   118.6 2853.93   130.4  2855.1   138.9  2856.5     147 2859.34     151 2859.39
   171.3  2858.6   199.6 2854.16   215.9 2856.03   219.9 2858.01   232.3 2868.92
   240.2 2872.03     257 2873.79   263.7 2875.25   291.2 2885.59   298.6 2887.63
   312.5 2886.67   323.2 2887.59   339.2 2893.48   363.2 2900.39   381.4 2904.45
#Mann= 3, -1 ,  0
       0     0.1       0  110.44   0.045       0   130.4     0.1       0
Bank Sta=110.44,130.4
XS Rating Curve= 0 ,0
Exp/Cntr(USF)=0,0
Exp/Cntr=0.3,0.1

Type RM Length L Ch R = 1 ,692     ,261.5,262.4,262.9
XS GIS Cut Line= 2
 2209223.4532075577950.5904048462209498.42408576578232.033436789
#Sta/Elev= 30
       0 2900.14     9.2 2898.83    20.4  2892.8    29.7 2886.28    44.8 2872.48
    56.1 2859.09    64.6 2850.55    67.4 2849.61   71.52 2850.55    76.3 2851.68
    98.3 2851.01   115.5 2853.12   121.1    2853   132.5 2850.58   138.1 2851.45
   149.4 2855.75     177 2856.98   191.9 2864.53   199.3  2866.8   207.1 2867.18
   234.3  2864.4   249.7 2866.16   264.3 2869.07   279.5  2876.4   288.8 2879.58
   299.3  2881.9   311.2 2882.68   321.6  2885.7     333 2886.91   393.5 2902.36
#Mann= 3, -1 ,  0
       0     0.1       0    64.6   0.045       0   71.52     0.1       0
Bank Sta=64.6,71.52
XS Rating Curve= 0 ,0
Exp/Cntr(USF)=0,0
Exp/Cntr=0.3,0.1

Type RM Length L Ch R = 1 ,429     ,139,143,145.4
XS GIS Cut Line= 4
2209120.51381204578045.575396354 2209091.2063986578186.261255722
2209204.79036104578298.0004653572209389.81983141578366.380921799
#Sta/Elev= 30
       0 2883.71      20 2877.56    48.6 2871.44   112.6  2865.5   150.7  2848.8
   160.6 2841.05   163.8 2839.46   177.6 2838.61   183.92839.449   195.6 2842.71
     203 2842.18   211.5 2840.02   222.8 2839.58   234.8 2841.58   257.3 2840.84
   262.4 2841.79   273.3 2849.11   279.1 2850.64     291  2851.9   333.1 2852.47
   346.8 2854.36   370.6  2862.4   387.7 2870.09   400.5 2871.69   407.8 2875.58
   417.5 2879.16   430.3 2881.36   477.2 2895.79   494.3 2897.46   500.3 2899.56
#Mann= 3, -1 ,  0
       0     0.1       0   163.8   0.045       0   183.9     0.1       0
Bank Sta=163.8,183.9
XS Rating Curve= 0 ,0
Exp/Cntr(USF)=0,0
Exp/Cntr=0.3,0.1

Type RM Length L Ch R = 1 ,286     ,79.5,78,73
XS GIS Cut Line= 4
2209085.64642764578044.8636482732209032.94692419578297.345540666
2209079.59347082578391.1827574022209361.66317288578462.113560818
#Sta/Elev= 30
       0  2882.8     8.5 2879.41    24.8 2877.91      33 2874.04    57.5 2868.71
   122.9  2864.7   135.2 2860.91   155.6 2849.38   184.2 2845.53   192.4 2842.76
   212.8 2841.33   225.1 2838.29   253.7 2839.52   289.92835.098     296 2834.63
  309.34  2835.1   333.7 2839.32   360.5  2838.4   379.8 2850.07   383.9 2850.76
   408.7    2847   433.4 2849.73   458.2 2846.06   473.6 2847.17   487.1 2852.18
   507.7 2864.08     520 2864.99   532.4 2870.98   602.5 2888.06   653.6 2905.12
#Mann= 3, -1 ,  0
       0     0.1       0   289.9   0.045       0  309.34     0.1       0
Bank Sta=289.9,309.34
XS Rating Curve= 0 ,0
Exp/Cntr(USF)=0,0
Exp/Cntr=0.3,0.1

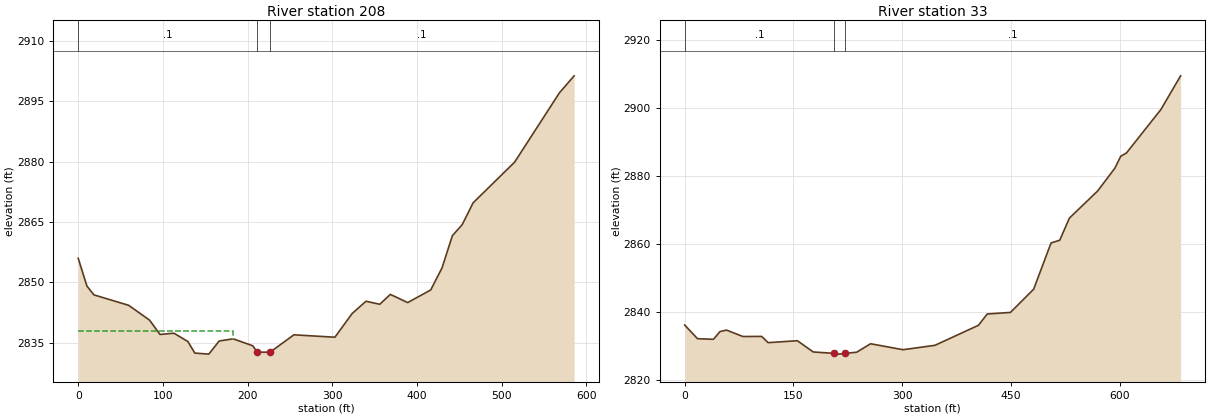
Type RM Length L Ch R = 1 ,208     ,168,175.4,174.8
XS GIS Cut Line= 4
2209034.66742352578179.1445724062208989.17341762578371.356747363
2209035.80477367578415.7134031232209353.12546487578479.973686466
#Sta/Elev= 30
       0 2855.95    10.3 2849.05    18.5 2846.86    59.6 2844.26    84.3 2840.57
    96.6 2837.02   113.1 2837.33   129.5 2835.26   137.7 2832.39   154.2 2832.13
   166.5  2835.4     183 2835.93     206 2834.22  211.47 2832.61   226.52832.611
   254.7 2836.93   303.1 2836.33   323.5 2842.23   339.8 2845.27   356.1 2844.52
   368.6 2846.98     389 2844.94   416.2 2848.07   429.6 2853.56   441.8 2861.56
   453.5 2864.34   466.3 2869.74   515.3 2879.84   568.3  2897.1   585.6  2901.3
#Mann= 3, -1 ,  0
       0     0.1       0  211.47   0.045       0   226.5     0.1       0
#XS Ineff= 2 , 0
           183.3 2837.97
Permanent Ineff=
       F       F
Bank Sta=211.47,226.5
XS Rating Curve= 0 ,0
Exp/Cntr(USF)=0,0
Exp/Cntr=0.3,0.1

Type RM Length L Ch R = 1 ,33      ,,,
XS GIS Cut Line= 4
2209004.40607709578294.0552735392208910.44563371578473.109388173
2208924.13922912578505.1990184012209370.74575354578521.534767936
#Sta/Elev= 30
       0 2836.18    17.7 2832.17    39.7 2831.99    48.7 2834.26    57.7 2834.69
    80.3 2832.81   106.2 2832.84   115.1    2831   155.4 2831.57   177.3 2828.27
   206.6 2827.84   212.7 2827.63  220.69 2827.83   237.2 2828.19   256.4 2830.68
   301.2 2828.93   345.2 2830.22   405.2 2836.11   417.3 2839.43   449.3 2839.89
   481.3 2846.71   505.3  2860.3   517.3 2861.11   530.6 2867.61   569.4 2875.55
   593.4  2882.3   601.4 2885.79   609.4 2886.78   656.8 2899.53     684 2909.43
#Mann= 3, -1 ,  0
       0     0.1       0   206.6   0.045       0  220.69     0.1       0
Bank Sta=206.6,220.69
XS Rating Curve= 0 ,0
Exp/Cntr(USF)=0,0
Exp/Cntr=0.3,0.1
LCMann Table=0

Chan Stop Cuts=-1
Use User Specified Reach Order=0
Composite Channel Slope=5